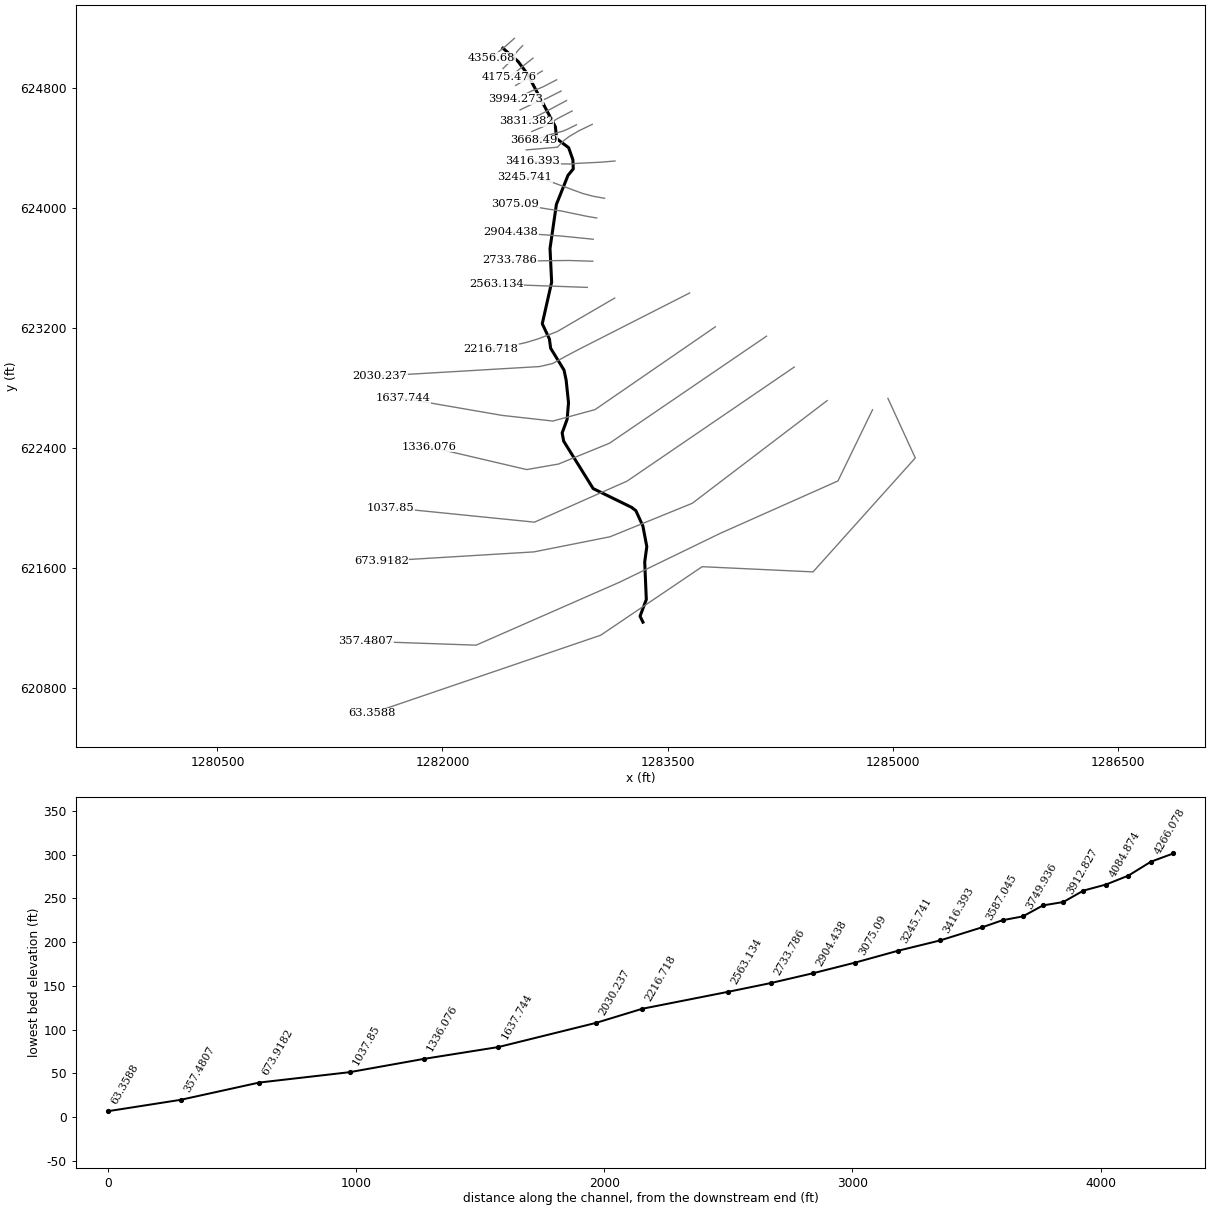
--- 584_ras.prj (project) ---

Proj Title=584
Current Plan=p01
Default Exp/Contr=0.3,0.1
English Units
Geom File=g01
Flow File=f01
Plan File=p01
Y Axis Title=Elevation
X Axis Title(PF)=Main Channel Distance
X Axis Title(XS)=Station
BEGIN DESCRIPTION:
RFD model 584 exported to HEC-RAS
END DESCRIPTION:

--- 584_ras.p01 (plan) ---

Plan Title=Plan 01
Program Version=4.10
Short Identifier=Plan 01
Geom File=g01
Flow File=f01
Subcritical Flow
Calc Critical at every XS
Secant Critical Depth

--- 584_ras.f01 (steady flow) ---

Flow Title=Flow 01
Program Version=5.01
Number of Profiles= 5
Profile Names=10yr,25yr,50yr,100yr,500yr
River Rch & RM=584,24, 4356.68
  397.28  476.31   568.5  609.47  719.36
River Rch & RM=584,24,4084.874
  406.35  488.79  583.83     628  744.41
River Rch & RM=584,24,3994.273
   415.9  501.98  600.05  647.66  771.11
River Rch & RM=584,24,3831.382
  422.85  511.61  611.89  662.06  790.73
River Rch & RM=584,24, 3668.49
  434.79  528.19  632.31  686.98  824.84
River Rch & RM=584,24,3416.393
  438.42  533.25  638.54   694.6  835.31
River Rch & RM=584,24,3245.741
  535.32   670.4   808.1  905.41 1130.86
River Rch & RM=584,24, 3075.09
  547.33  687.66  829.52  932.46 1169.55
River Rch & RM=584,24,2904.438
  553.43  696.46  840.44  946.29 1189.41
River Rch & RM=584,24,2733.786
  559.44  705.13  851.21  959.94 1209.04
River Rch & RM=584,24,2563.134
  563.39  710.84   858.3  968.95 1222.01
River Rch & RM=584,24,2216.718
     669  865.55 1051.08 1217.13 1585.87
River Rch & RM=584,24,2030.237
  672.75  871.12 1058.05 1226.21  1599.4
River Rch & RM=584,24,1637.744
  677.59  878.31 1067.02 1237.92 1616.87
River Rch & RM=584,24,1336.076
  683.47  887.05 1077.95  1252.2 1638.21
River Rch & RM=584,24, 1037.85
  688.55  894.61 1087.41 1264.58 1656.72
River Rch & RM=584,24,673.9182
  692.15  899.97 1094.11 1273.35 1669.87
River Rch & RM=584,24,357.4807
  693.22  901.57 1096.11 1275.97  1673.8
River Rch & RM=584,24, 63.3588
  699.61  911.09 1108.03  1291.6 1697.24
Boundary for River Rch & Prof#=584,24,1
Up Type= 0
Dn Type= 2
Boundary for River Rch & Prof#=584,24,2
Up Type= 0
Dn Type= 2
Boundary for River Rch & Prof#=584,24,2
Up Type= 0
Dn Type= 2
Boundary for River Rch & Prof#=584,24,2
Up Type= 0
Dn Type= 2
Boundary for River Rch & Prof#=584,24,2
Up Type= 0
Dn Type= 2

--- 584_ras.g01 (geometry) ---

Geom Title=584
Program Version=4.10

River Reach=584,24
Reach XY= 30
1282402.54323789625062.6779931781282504.20987192624973.511349976
1282565.87651798624891.0113726561282752.54311916624538.511471838
1282760.87644774624459.3448284421282840.87642235624399.344843879
1282869.20974496624318.5115337671282871.70974246624257.678218395
1282836.70975152624215.1782320441282759.20976868 624021.01162526
1282716.70977262623727.6783803111282727.54309613  623502.6784468
1282665.04310644623226.0118641261282712.54308939623124.345226228
 1282720.8764185623062.6785776321282810.04305449622916.845284984
1282824.20971507622850.1786376681282840.04303923622698.512015596
1282830.87637207622589.3453816181282797.66659141622498.146201566
1282807.56217545622443.463687032 1283004.1767588622127.057437047
1283259.38509211622002.4914648231283288.89898103621979.922020376
1283335.77398103621877.4914648231283361.81564769621740.338687047
1283347.92675883621637.9081314951283358.57490698621387.618779644
1283316.90824026621276.507668525 1283336.0054625621236.577112958

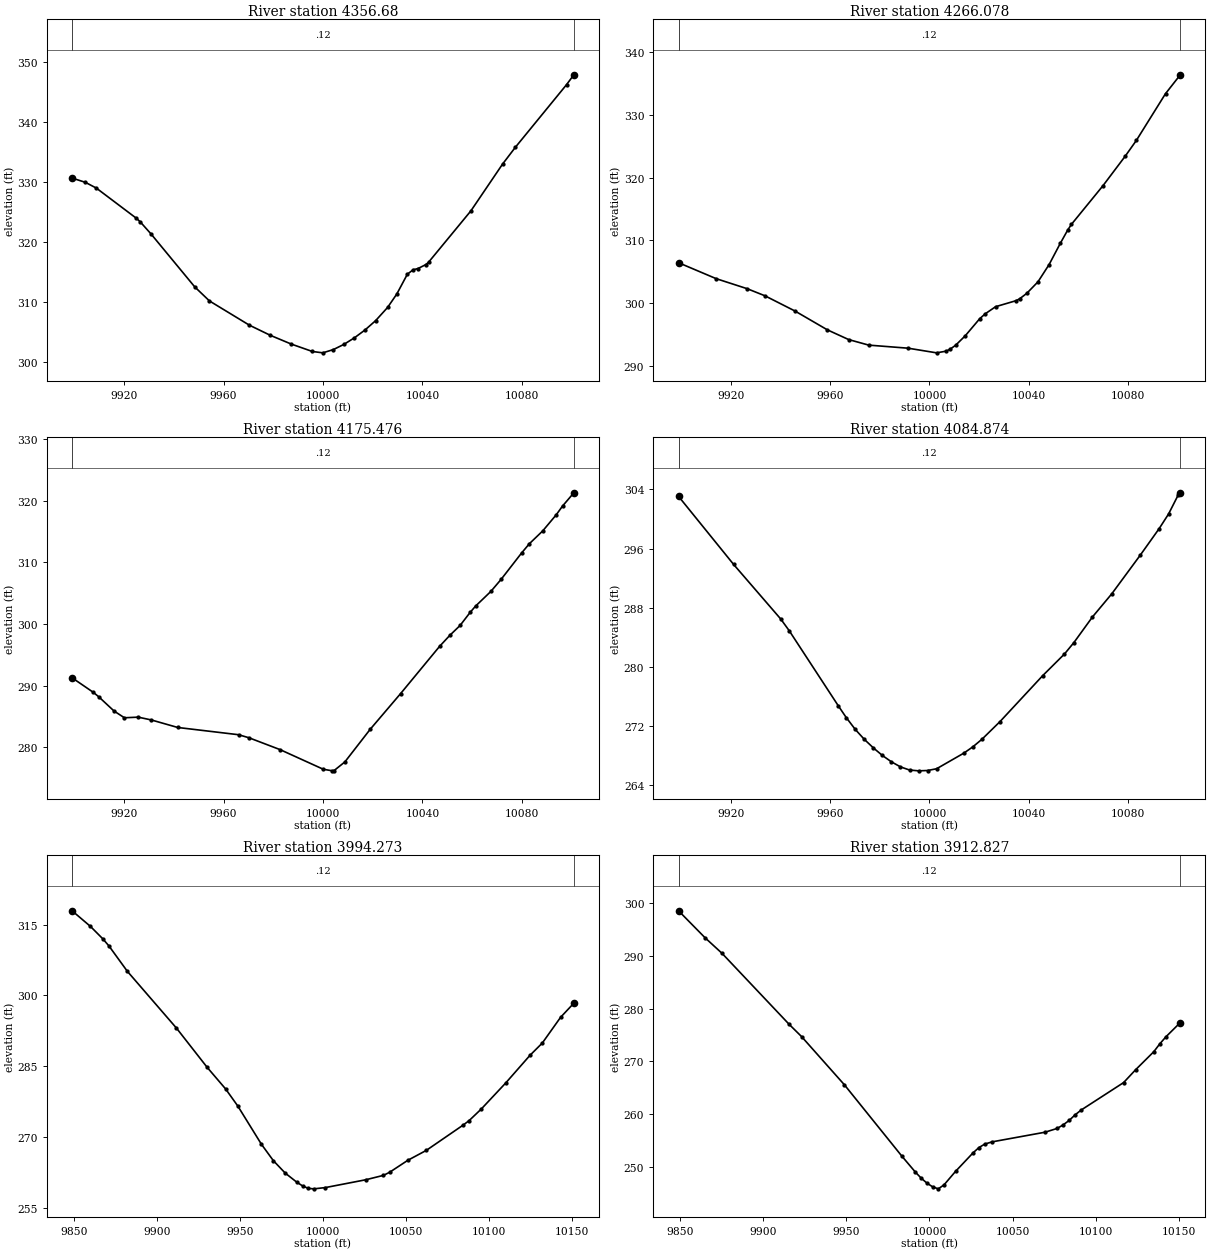
Type RM Length L Ch R = 1 , 4356.68,90.601800,90.601800,90.601800
XS GIS Cut Line= 5
1282479.37549838625128.1025219781282425.46455966625079.900940517
1282403.94557264625062.4950799091282402.36032463625061.275658434
1282325.35492062624997.492698794
#Sta/Elev= 30
9899.006 330.6199904.356329.90849908.757328.95489924.768323.96569926.361323.3716
9930.762321.33289948.366312.51999954.302310.17329970.371306.14149978.849304.4451
9987.289  302.999995.728301.7638 9999.93301.537410004.16302.077510008.42302.9423
10012.68304.042410016.94305.3463 10021.2 306.89510026.02309.095110029.72311.3248
10033.98314.630610036.31315.363210038.24315.562610041.45316.2308 10042.5316.6122
10059.54325.159610072.31332.954310077.45335.743610098.03346.151710100.99347.8051
#Mann= 3 , 0 , 0
9899.006    0.12       09899.006    0.12       010100.99    0.12       0
#XS Ineff= 2 , 0
       0                               0
Bank Sta=9899.006,10100.99
Exp/Cntr=0.3,0.1

Type RM Length L Ch R = 1 ,4266.078,90.601700,90.601700,90.601700
XS GIS Cut Line= 6
1282534.29032252625079.0368354451282509.75911319625054.431612212
1282488.88536606625030.5090150621282461.18215764624987.623351264
1282448.22696348624970.8341221021282403.39447589 624926.41275285
#Sta/Elev= 30
9899.024306.43659914.213 303.886 9926.69302.28439933.769301.16419945.869 298.733
9958.931295.72259967.489294.17329975.577293.28669991.431 292.79610002.86292.0554
 10006.7292.320310008.22 292.61210010.54293.267410014.38294.763110020.22297.4957
10022.49298.294710026.63299.419910034.92300.385510036.33300.686210039.17301.5487
10043.67303.382610048.17306.147810052.67309.532810055.66 311.65710057.17312.5703
 10069.8318.706410078.78323.430110083.27325.947410095.01333.414910100.97336.4261
#Mann= 3 , 0 , 0
9899.024    0.12       09899.024    0.12       010100.97    0.12       0
#XS Ineff= 2 , 0
       0                               0
Bank Sta=9899.024,10100.97
Exp/Cntr=0.3,0.1

Type RM Length L Ch R = 1 ,4175.476,90.601800,90.601800,90.601800
XS GIS Cut Line= 6
1282603.48670476624996.165638651 1282537.1917435624943.975484383
1282525.39878796 624933.736651711282523.98457436624932.322438187
1282501.00356868624912.7090408611282445.52594322624870.398409291
#Sta/Elev= 30
9899.009291.26649907.548288.9084 9909.72288.19389915.899285.87739920.074284.7808
9925.632284.88129930.936284.42469941.544283.20659966.005282.0333 9970.18281.5415
9982.707 279.61810000.13276.430110003.83276.1736 10004.5276.226410008.82277.6233
10018.99282.903710031.21288.686110046.92296.354410051.05298.147310055.18299.7499
 10059.3301.906410061.41302.889410067.56305.269110071.68307.219710079.93311.5006
10083.05313.000410088.46315.094810093.87317.694510096.44319.128410100.98321.2732
#Mann= 3 , 0 , 0
9899.009    0.12       09899.009    0.12       010100.98    0.12       0
#XS Ineff= 2 , 0
       0                               0
Bank Sta=9899.009,10100.98
Exp/Cntr=0.3,0.1

Type RM Length L Ch R = 1 ,4084.874,90.601800,90.601800,90.601800
XS GIS Cut Line= 6
1282665.15491453624910.230368595 1282610.4950187624878.449404594
1282577.31931521624862.6291597831282575.51276018624861.771046207
1282535.45162101624842.2443657671282487.70525719624814.117412527
#Sta/Elev= 30
9899.018303.06549921.186293.85159940.162 286.4589943.574284.87349963.308274.7158
9966.538273.10819970.173271.50349973.808270.16189977.442269.00939981.077267.9827
9984.712 267.1249988.347266.44029991.981 266.0169995.616265.90499999.251265.9494
10002.89266.187510013.84268.301310017.49269.158510021.14270.180110028.44272.5849
10045.57278.786910054.35281.723710058.16283.277410065.63286.746310073.39289.8715
10084.82295.089710092.43298.685910096.24300.676310100.05303.202410100.98303.5517
#Mann= 3 , 0 , 0
9899.018    0.12       09899.018    0.12       010100.98    0.12       0
#XS Ineff= 2 , 0
       0                               0
Bank Sta=9899.018,10100.98
Exp/Cntr=0.3,0.1

Type RM Length L Ch R = 1 ,3994.273,81.445500,81.445500,81.445500
XS GIS Cut Line= 6
1282760.80649876624851.6632934721282674.23576484624806.768085411
 1282641.8251135624792.8577563161282612.14220644624784.317757274
1282591.97188294624776.2266386531282487.95609863624723.724173943
#Sta/Elev= 30
9849.022317.95599860.095 314.6379867.486312.02079871.182310.51369882.269305.1281
9911.835 293.0799930.314284.75529941.401280.18449948.717276.57059962.997268.4297
9970.138 264.9749977.278 262.3389984.317260.38939987.748259.61559991.179259.0876
9994.609258.999710001.42259.266910025.73260.923110036.41261.861210040.08262.5105
10051.11265.065110062.13 267.14410084.18272.480810087.86273.444610095.21275.9115
10109.91281.430710124.61287.331310131.96 289.91210142.98295.375110150.95298.3686
#Mann= 3 , 0 , 0
9849.022    0.12       09849.022    0.12       010150.95    0.12       0
#XS Ineff= 2 , 0
       0                               0
Bank Sta=9849.022,10150.95
Exp/Cntr=0.3,0.1

Type RM Length L Ch R = 1 ,3912.827,81.445500,81.445500,81.445500
XS GIS Cut Line= 6
1282790.72864516624776.9353667041282693.13547761624727.361566332
1282670.22219872624717.6259950721282641.08184947624708.528801652
1282618.84870505624699.6953036281282516.76079602624650.900567414
#Sta/Elev= 30
9849.023298.51249864.945293.4204 9875.21290.45569915.655277.00279923.048274.7116
9948.807 265.5969983.381252.09539991.601249.04399995.047247.91879998.492 246.983
10001.91246.279410005.34245.896810008.77246.645810015.69249.190910026.28252.7157
10029.81253.711810033.34 254.37110037.83254.793710069.57256.612910076.84257.3257
10080.48     25810084.11  258.8510087.75259.919610091.39260.826310116.84266.0018
10124.11 268.44410135.02271.849110138.66273.3447 10142.3274.659910150.98277.3663
#Mann= 3 , 0 , 0
9849.023    0.12       09849.023    0.12       010150.98    0.12       0
#XS Ineff= 2 , 0
       0                               0
Bank Sta=9849.023,10150.98
Exp/Cntr=0.3,0.1

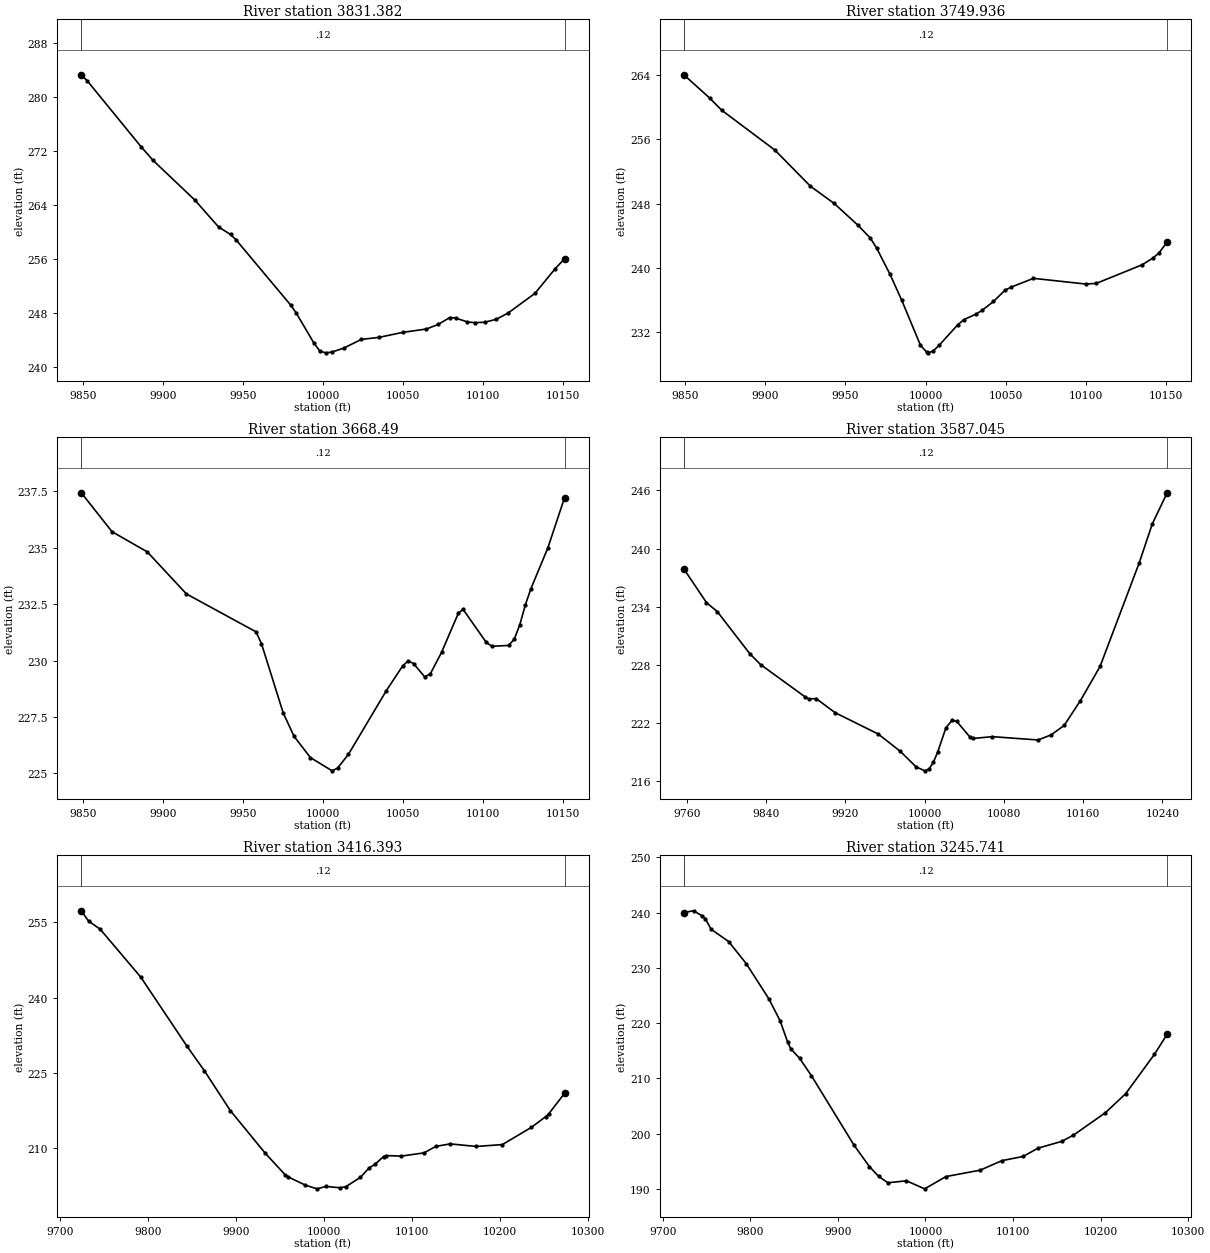
Type RM Length L Ch R = 1 ,3831.382,81.445600,81.445600,81.445600
XS GIS Cut Line= 5
1282826.57479133624713.4920431581282694.40868425624642.575566969
1282692.57636955624641.7739293531282640.04260036624614.201114278
1282558.47369866624574.642266734
#Sta/Elev= 30
 9849.01283.29619852.891282.3614  9886.4272.61659893.847270.6034 9919.91264.7279
9934.803260.7189 9942.25259.60989945.973258.74479979.883249.12499983.206247.9992
9994.376243.50039998.099242.307210001.74242.052210005.44242.162210012.85242.7344
10023.97244.040710035.09244.350310049.91245.091610064.66245.586310071.95246.2606
10079.24247.287110082.89247.213110090.18246.638710094.89246.526410101.12246.5909
10108.41247.036910115.71247.962710132.48250.873710144.88 254.47110150.99256.0254
#Mann= 3 , 0 , 0
 9849.01    0.12       0 9849.01    0.12       010150.99    0.12       0
#XS Ineff= 2 , 0
       0                               0
Bank Sta=9849.01,10150.99
Exp/Cntr=0.3,0.1

Type RM Length L Ch R = 1 ,3749.936,81.445500,81.445500,81.445500
XS GIS Cut Line= 6
1282863.74475196624643.8613482991282766.36649923624593.030477836
1282732.72425202624571.1870380391282731.14168198624569.964143084
1282705.39006128624553.8024164981282595.40692725624507.002357642
#Sta/Elev= 30
9849.042264.00759865.221261.10949872.623259.61499905.931254.64829928.137250.1551
 9942.94 248.0199957.744245.32149965.502243.71929969.414242.49529977.827239.2111
9985.061236.02799996.796230.416610000.81229.5119 10001.7229.4492 10004.7229.6727
10008.57230.395610020.21232.951610024.06233.5864 10031.4234.244510035.34234.7282
10042.47  235.8310049.61 237.22410053.17237.589710067.43238.7073   10100238.0029
10106.65238.077810135.18240.3795 10141.9241.204310145.87241.866810150.93243.2421
#Mann= 3 , 0 , 0
9849.042    0.12       09849.042    0.12       010150.93    0.12       0
#XS Ineff= 2 , 0
       0                 10068.8       0
Bank Sta=9849.042,10150.93
Exp/Cntr=0.3,0.1

Type RM Length L Ch R = 1 , 3668.49,81.445500,81.445500,81.445500
XS GIS Cut Line= 6
1282892.84525648624552.0274549361282834.03016822 624522.73041945
1282801.54847488624509.0169365251282754.24650001624496.272992827
1282700.08660166624482.3193672921282609.84837335  624449.4328903
#Sta/Elev= 30
9849.046237.43949868.258235.7147 9890.25234.82139914.753232.95429958.215231.2759
9961.612230.75059975.204227.67799981.999226.63919992.193 225.70110005.76225.1134
10009.15225.236310015.93225.844210039.64 228.67210049.81229.7647 10053.2 229.986
10056.63229.868510063.62229.273810067.11229.417810074.09230.361110084.57232.0955
10087.49232.276310102.03230.807810105.52230.6335   10116230.672710119.49230.9458
10122.98231.589710126.47232.474710129.96233.195410140.44234.983110150.97237.2292
#Mann= 3 , 0 , 0
9849.046    0.12       09849.046    0.12       010150.97    0.12       0
#XS Ineff= 2 , 0
       09952.873        10058.06       0
Bank Sta=9849.046,10150.97
Exp/Cntr=0.3,0.1

Type RM Length L Ch R = 1 ,3587.045,170.651800,170.651800,170.651800
XS GIS Cut Line= 6
1282997.96634141624554.6832815561282910.86333278624512.676905707
1282846.16958067624474.8987072561282808.67611939624446.594672054
1282765.89408278624402.4711841341282558.81072873624384.307147697
#Sta/Elev= 30
9756.754 237.9149779.638234.42979790.565233.50549823.347229.16329834.274  228.04
9879.039  224.729882.839224.50279890.437224.52559909.433223.08279953.099220.8709
9975.351219.08769991.191217.498210000.06217.078110004.42  217.28 10008.8217.9769
10013.17219.041410021.41221.520410027.52222.278210032.34222.181510045.26220.6072
10048.55220.416110068.31220.603310114.42220.261510127.59220.784810140.77221.7612
10157.23 224.327   10177227.841510216.52238.518810229.69242.530710244.75245.7581
#Mann= 3 , 0 , 0
9756.754    0.12       09756.754    0.12       010244.75    0.12       0
#XS Ineff= 2 , 0
       09917.644        10031.28       0
Bank Sta=9756.754,10244.75
Exp/Cntr=0.3,0.1

Type RM Length L Ch R = 1 ,3416.393,170.651800,170.651800,170.651800
XS GIS Cut Line= 6
 1283149.6222581624310.5344512911283056.64685929624302.541948691
1282899.66438514624294.8382810061282857.80419561624290.456902534
1282786.57987007624291.3306509411282601.72088498624307.974682406
#Sta/Elev= 30
9724.026257.32369732.283255.27879745.454 253.6629791.555 244.1289844.176230.3419
9863.885225.47389893.448217.51279932.865209.07739955.858204.70119959.143204.3035
9978.868202.64629992.054201.917210001.97202.393710018.45202.129210025.02 202.364
10041.42204.226510051.26206.100110057.83 206.78510067.67208.354410070.95208.5412
10087.84 208.44110113.71209.082510126.88210.371910143.35210.8738   10173210.3629
10202.65210.733810235.59214.156410252.06216.314210255.35216.848610273.45  220.97
#Mann= 3 , 0 , 0
9724.026    0.12       09724.026    0.12       010273.45    0.12       0
#XS Ineff= 2 , 0
       0                10068.95       0
Bank Sta=9724.026,10273.45
Exp/Cntr=0.3,0.1

Type RM Length L Ch R = 1 ,3245.741,170.651900,170.651900,170.651900
XS GIS Cut Line= 6
1283080.28509344624061.9936555091283006.63664246624075.090829817
1282935.23988953624093.8281275881282695.63345846 624181.97732779
1282619.43036174624196.5547799011282549.48318429624201.746243468
#Sta/Elev= 30
9724.056240.01259735.297240.32679745.294239.36719748.626238.88169755.291236.9721
9775.285234.76059795.279230.78189821.152224.40279834.076220.40669842.702216.5371
9846.093215.37519856.269213.64819869.837210.47799918.349197.94519935.955194.0652
9946.537192.28599957.118191.13319978.282 191.4849999.023190.033410023.39192.2557
10062.45193.4095 10087.3195.1358 10111.4195.8893 10128.6197.396210155.51198.6126
10168.96199.746510205.48203.807310228.51207.232610261.41214.356610275.93218.0012
#Mann= 3 , 0 , 0
9724.056    0.12       09724.056    0.12       010275.93    0.12       0
#XS Ineff= 2 , 0
       0                10062.62       0
Bank Sta=9724.056,10275.93
Exp/Cntr=0.3,0.1

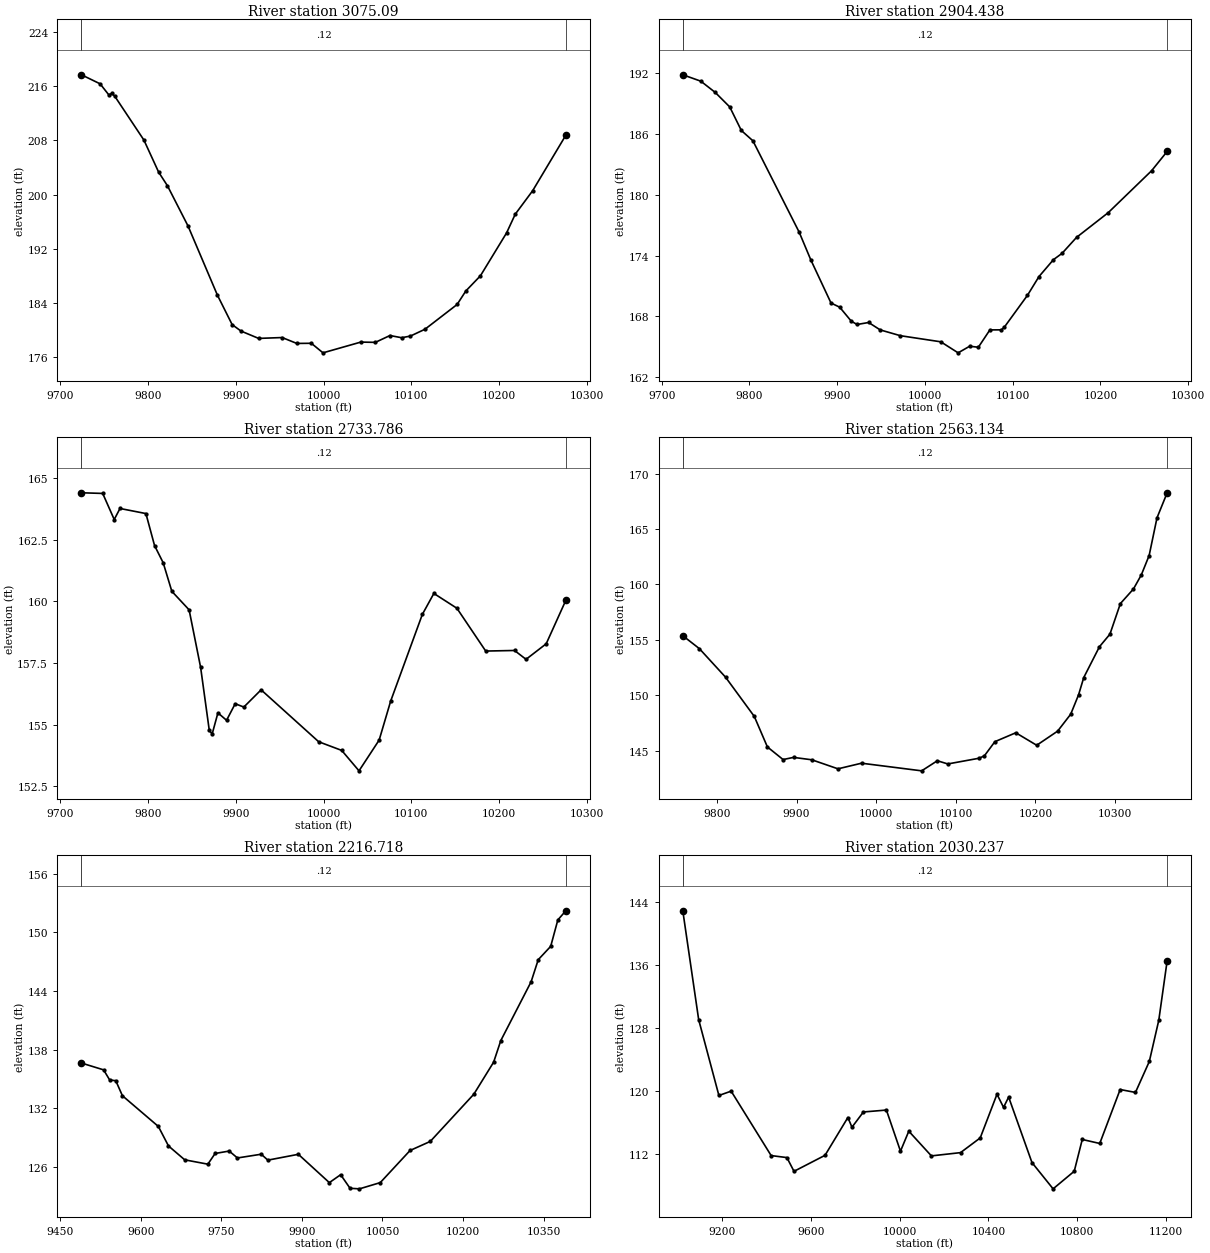
Type RM Length L Ch R = 1 , 3075.09,170.651800,170.651800,170.651800
XS GIS Cut Line= 6
1283027.81877499623930.5695850621282956.97892525623942.885279905
 1282794.2530129623976.8724111591282707.29463815623989.465456888
1282572.70270831624011.9023314181282483.80171801624022.292651649
#Sta/Elev= 30
9724.019 217.687 9745.27216.3524 9755.26 214.711 9758.59214.93359761.921 214.532
9795.221208.04239811.975203.31339822.029201.29789845.491195.35629879.007185.1356
9895.765180.7977 9905.82179.8474 9925.93178.76279952.743178.88989969.425 178.021
 9986.01178.04169999.278176.631410042.36178.218410058.96178.179410075.59179.1873
10088.89178.863910098.87179.1062 10115.5180.115210152.09183.769810162.07185.7676
 10178.7188.009510208.48194.338510218.39197.108410238.21200.569310275.98208.7571
#Mann= 3 , 0 , 0
9724.019    0.12       09724.019    0.12       010275.98    0.12       0
#XS Ineff= 2 , 0
       0                               0
Bank Sta=9724.019,10275.98
Exp/Cntr=0.3,0.1

Type RM Length L Ch R = 1 ,2904.438,170.651800,170.651800,170.651800
XS GIS Cut Line= 5
1283004.37164821623789.0476631791282784.40205397623810.948170725
1282730.58444846623814.5548315261282728.58953106623814.697325684
1282454.44294709623836.158405284
#Sta/Elev= 30
9724.005191.87149744.561191.23869761.046190.12169777.532188.6908 9790.72186.3659
9803.908185.34669856.661176.31239869.849173.58749892.929169.3137 9902.82 168.901
9916.008167.52049922.602167.1921 9935.79  167.399948.968166.65829971.985 166.085
10018.03165.481410037.78164.391210050.94 165.04510060.82164.943310073.98166.6581
10087.14166.664210090.43166.929410116.76170.072110129.92171.929210146.38 173.598
10156.25 174.22610172.71 175.80110208.91178.250210258.27182.388710275.99184.2947
#Mann= 3 , 0 , 0
9724.005    0.12       09724.005    0.12       010275.99    0.12       0
#XS Ineff= 2 , 0
       09901.988                       0
Bank Sta=9724.005,10275.99
Exp/Cntr=0.3,0.1

Type RM Length L Ch R = 1 ,2733.786,170.651800,170.651800,170.651800
XS GIS Cut Line= 6
1283001.56556283623642.2673279561282842.28101308623647.435650879
 1282726.6696243623646.193128322 1282724.6708123623646.124203826
1282619.82598085623644.4621679651282449.76978783623649.451531302
#Sta/Elev= 30
9724.014164.39699748.237164.37059761.368163.31299767.933163.76049797.476163.5545
9807.324162.25719817.171161.55889827.019160.40189846.714159.65059859.844157.3147
9869.692154.76599872.975154.6167 9879.54155.47379889.385155.17259899.228155.8442
9909.071155.70949928.757156.40779994.377154.302610020.63153.951210040.32153.1234
10063.28154.370810076.41155.9518 10112.5159.466210125.63160.315510151.89159.7147
10184.71157.979710217.54158.003210230.67157.644210253.64158.274310275.99160.0357
#Mann= 3 , 0 , 0
9724.014    0.12       09724.014    0.12       010275.99    0.12       0
#XS Ineff= 2 , 0
       0 9926.65        10132.01       0
Bank Sta=9724.014,10275.99
Exp/Cntr=0.3,0.1

Type RM Length L Ch R = 1 ,2563.134,346.416400,346.416400,346.416400
XS GIS Cut Line= 2
1282965.38139588623467.979540974 1282357.6388537623489.775897712
#Sta/Elev= 30
9757.217155.36699778.066154.19929810.896151.62569847.008 148.0849863.423145.3337
 9883.12144.19459896.252144.38959919.233 144.1739952.062143.35829981.609143.8649
10057.12143.176310076.81144.086410089.95143.797810129.34144.314910135.91144.5348
10149.04145.8071 10175.3146.611110201.57145.483810227.83146.758610244.24148.2841
10254.09150.027410260.66151.597210280.36154.375710293.49 155.50510306.62158.2675
10323.03159.583410332.88160.848810342.73 162.60310352.58165.999110365.35168.2636
#Mann= 3 , 0 , 0
9757.217    0.12       09757.217    0.12       010365.35    0.12       0
#XS Ineff= 2 , 0
       09938.861        10118.91       0
Bank Sta=9757.217,10365.35
Exp/Cntr=0.3,0.1

Type RM Length L Ch R = 1 ,2216.718,186.480700,186.480700,186.480700
XS GIS Cut Line= 6
1283147.72782943623396.7333629731282763.99161163623173.309893191
1282635.53329629623124.2583676731282553.04687095623099.420934796
1282440.12232935 623074.910933421282322.89360675623057.372006446
#Sta/Elev= 30
9489.518136.62099530.787135.92339542.115134.88569553.442134.81369565.821133.2737
9632.734  130.139651.613128.13279681.819126.71149724.902126.26659738.456127.3622
9764.672127.6096 9779.99126.90219824.327127.28569836.627126.67929893.422127.2766
 9951.16124.37699972.198125.1885 9989.73123.795510007.29123.740710045.97124.3783
10101.45127.667110139.13128.596510220.28133.434710257.08136.711810270.47138.9246
10326.88144.941510340.15147.204410363.37148.571310376.64151.2745 10391.5152.2126
#Mann= 3 , 0 , 0
9489.518    0.12       09489.518    0.12       0 10391.5    0.12       0
#XS Ineff= 2 , 0
       09928.201        10098.89       0
Bank Sta=9489.518,10391.5
Exp/Cntr=0.3,0.1

Type RM Length L Ch R = 1 ,2030.237,392.492600,392.492600,392.492600
XS GIS Cut Line= 6
1283647.38060716623430.8045435251282913.87366274623057.540654629
1282825.04046255623010.7519241571282733.05557045622960.192315891
1282646.94657943622940.3531546291281581.40838498622877.419126853
#Sta/Elev= 30
9021.648142.89819093.238129.06839184.446119.43329239.664 119.9849420.043111.8001
9491.107111.54459523.117109.79789663.002111.83189766.076116.63559784.482115.4033
9836.018117.33899939.782117.581910003.25112.357810040.79 114.89910142.64111.7592
 10274.1112.174210362.84114.042410438.43 119.59110468.01117.924910491.02119.2295
10596.19110.9116 10691.5107.573910786.81109.809710822.96113.845210901.84113.3381
10993.86120.189311062.88119.823211125.32123.753611168.05128.992811205.79136.5484
#Mann= 3 , 0 , 0
9021.648    0.12       09021.648    0.12       011205.79    0.12       0
#XS Ineff= 2 , 0
       09938.149        10254.82       0
Bank Sta=9021.648,11205.79
Exp/Cntr=0.3,0.1

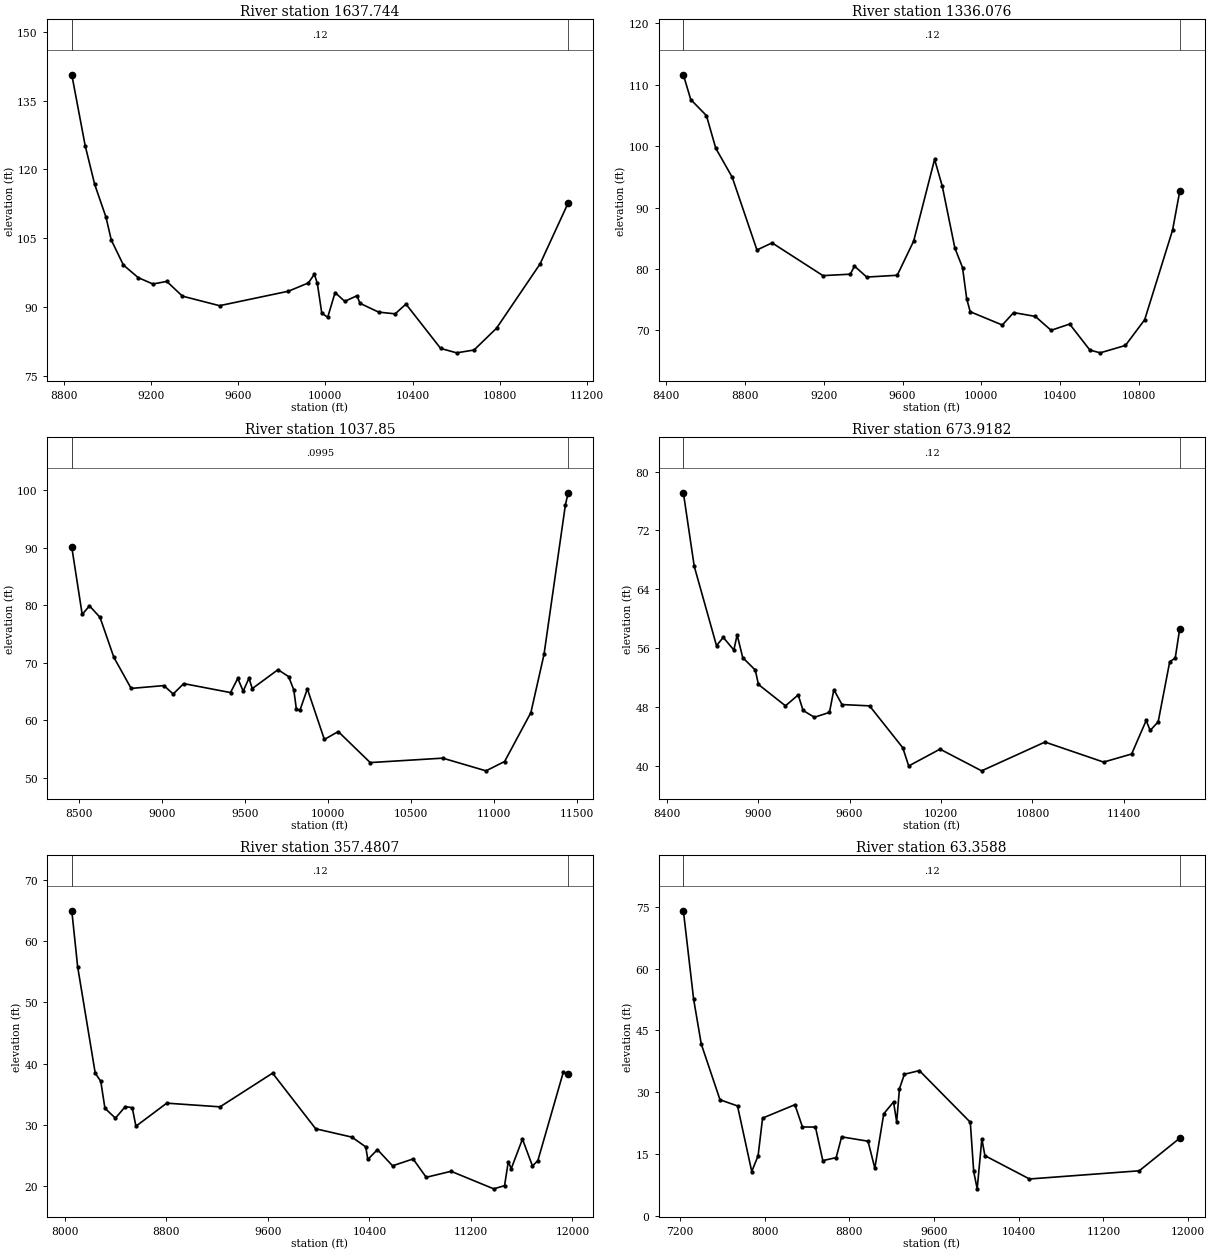
Type RM Length L Ch R = 1 ,1637.744,301.668600,301.668600,301.668600
XS GIS Cut Line= 5
1283818.70783341623205.3099991231283016.62450004 622653.22666578
1282735.68919486622577.184026778 1282398.1055918622614.780702263
1281734.91114739622729.364035591
#Sta/Elev= 30
8836.458140.62898897.974125.14168941.572116.70538993.563109.53429017.461104.6015
9073.22199.130519140.93196.38987 9208.6494.989319272.36795.555249344.05992.34034
9514.43490.259559830.46993.417589922.23995.229829949.43197.124749963.02695.13999
 9983.4288.6508610010.6187.72494 10044.693.1316610088.7991.2044810145.2692.43754
10158.4790.78633 10244.388.8586610320.2288.4821710369.7490.6106910528.9480.93599
10602.1979.97465 10682.180.5909110785.3185.3451710985.0799.3652311113.92112.6583
#Mann= 3 , 0 , 0
8836.458    0.12       08836.458    0.12       011113.92    0.12       0
#XS Ineff= 2 , 0
       09954.705        10383.81       0
Bank Sta=8836.458,11113.92
Exp/Cntr=0.3,0.1

Type RM Length L Ch R = 1 ,1336.076,298.226200,298.226200,298.226200
XS GIS Cut Line= 5
1284159.85366669623142.8099991231283112.97866672622429.268332452
1282773.56721947622290.7330478731282561.30003628622253.669591144
1281908.52225849622406.447368905
#Sta/Elev= 30
8487.443111.62598524.871107.59198604.621104.97288651.92599.659358735.30494.94709
8860.93283.093948937.79784.249499195.87678.917259334.84179.149999356.07880.46209
 9418.2278.680039573.06878.975269656.44784.543289762.65197.85445 9801.6393.48009
9865.41583.424919904.39580.235559925.65675.145899943.37473.0374310106.3870.87184
10163.8772.8991710273.7872.2752710353.9170.0113610448.2671.0272510550.8866.79042
10603.2666.34147 10731.3 67.546410829.0171.7322710970.5386.3147311006.8692.63076
#Mann= 3 , 0 , 0
8487.443    0.12       08487.443    0.12       011006.86    0.12       0
#XS Ineff= 2 , 0
       09941.224        10172.89       0
Bank Sta=8487.443,11006.86
Exp/Cntr=0.3,0.1

Type RM Length L Ch R = 1 , 1037.85,363.931400,363.931400,363.931400
XS GIS Cut Line= 4
1284344.74950007622937.0808324661283230.16616669622176.664165795
1282612.97866672621903.2266657951281651.57781407622000.197368905
#Sta/Elev= 30
 8455.6790.116438518.35478.403318562.04279.910628625.58877.911828708.993 70.9497
 8813.1665.531579010.83866.021539066.44164.554379129.98766.369019411.97464.80534
9455.66267.273689488.44965.05592 9523.1867.313429543.03965.500799698.021 68.7899
9762.05767.588749793.25265.272299808.73461.945089830.26461.715479874.86965.45381
9977.38956.6464910061.1658.01293 10253.7 52.616410690.8253.3874710951.32 51.1782
11063.4452.8030611221.7261.3178711300.8671.4438311429.4697.4362911446.2799.59766
#Mann= 3 , 0 , 0
 8455.67  0.0995       0 8455.67  0.0995       011446.27  0.0995       0
#XS Ineff= 2 , 0
       0 9696.56        10157.35       0
Bank Sta=8455.67,11446.27
Exp/Cntr=0.3,0.1

Type RM Length L Ch R = 1 ,673.9182,316.437500,316.437500,316.437500
XS GIS Cut Line= 5
1284563.49950004622713.1224991381283664.74171832622028.894821316
1283116.82950532621805.8169967381282609.91114739621705.058480039
1281592.98406407621643.426535591
#Sta/Elev= 30
8509.26677.108248580.47167.130928726.70956.331098770.92957.45699 8840.4555.73975
8862.11557.795188898.75454.709818981.22253.009549001.839  51.0589179.14548.15428
9262.91649.636169294.60147.525329368.82246.602489467.78347.259269496.64750.34309
9550.25148.328589731.00748.149359948.84942.460579987.81539.9812210193.2742.26776
10466.2939.3192310882.0343.2311511266.5940.5077311450.6541.6085411545.9746.16108
11572.2744.8033511624.8645.9884111700.4554.1458811736.6154.6396311766.05 58.6229
#Mann= 3 , 0 , 0
8509.266    0.12       08509.266    0.12       011766.05    0.12       0
#XS Ineff= 2 , 0
       09669.359        10302.08       0
Bank Sta=8509.266,11766.05
Exp/Cntr=0.3,0.1

Type RM Length L Ch R = 1 ,357.4807,294.121900,294.121900,294.121900
XS GIS Cut Line= 6
1284866.45088893622652.3586102281284635.89930859622177.790412083
1283853.35455483621829.5979677441283181.62112531 621503.62171784
 1282223.9965632621083.3089362231281488.84672225621108.955832452
#Sta/Elev= 30
8054.13164.969828100.18355.845048238.78838.459498282.55837.116778315.38532.71712
8397.98231.101098475.87632.991728530.58832.811038559.76829.787898802.67233.55134
9222.81332.950759636.86538.450889976.53829.3677410261.8128.00777 10371.526.40652
10387.3624.3533510463.6125.9650810582.5323.3206310744.6224.4394610847.8821.44302
11043.72 22.422111380.0619.5585111465.4120.0721911494.9624.0022511517.9422.83836
11606.5827.6868611685.3623.2926411728.0424.1689811928.2938.58787 11966.738.38823
#Mann= 3 , 0 , 0
8054.131    0.12       08054.131    0.12       0 11966.7    0.12       0
#XS Ineff= 2 , 0
       0 9595.32        10193.23       0
Bank Sta=8054.131,11966.7
Exp/Cntr=0.3,0.1

Type RM Length L Ch R = 1 , 63.3588,0.000000,0.000000,0.000000
XS GIS Cut Line= 6
1284969.05306089622728.4029231521285151.34472755 622331.26750648
1284469.92111644621571.7188953761283730.77604446621606.384376198
1283054.35559183621149.5029244721281526.57781407620628.669591129
#Sta/Elev= 30
7233.37174.082567330.13252.617397402.33141.695077579.219 28.14867744.58426.64819
7879.071 10.71147938.843 14.5263 7981.3223.690418286.46826.942978357.74821.53157
8480.50921.510038549.857 13.36198675.89814.084858727.77219.13391  8976.8 18.0739
9041.05511.512439125.46824.74574 9217.7227.621259247.37222.80705 9273.7330.84384
9320.35434.351059461.73935.235859942.44522.682649974.55110.7164110007.566.497935
10051.5318.6396810080.3114.5656710501.318.89390911537.7110.8840411919.6818.81064
#Mann= 3 , 0 , 0
7233.371    0.12       07233.371    0.12       011919.68    0.12       0
#XS Ineff= 2 , 0
       09452.409        10083.15       0
Bank Sta=7233.371,11919.68
Exp/Cntr=0.3,0.1